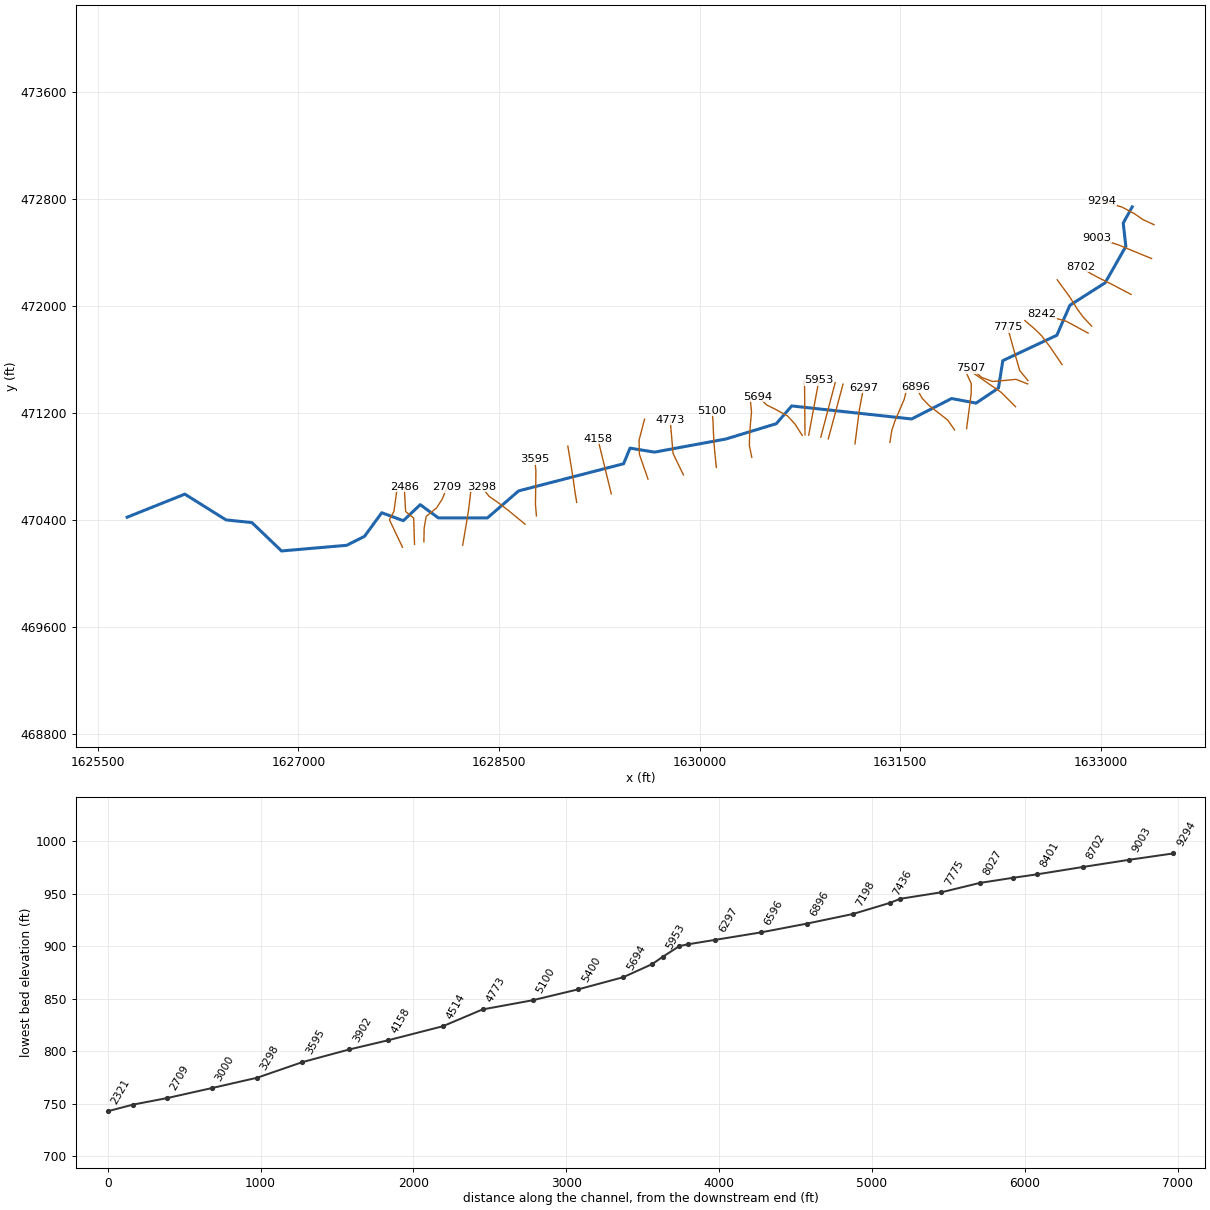
--- MdleBwmRn.prj (project) ---

Proj Title=MdleBwmRn
Current Plan=p01
Default Exp/Contr=0,0
English Units
Geom File=g01
Flow File=f01
Plan File=p01
BEGIN DESCRIPTION:
---------- MODELED AS PART OF WVEM CTP PROGRAM, 2025----------
Stream Name: Middle Bowman Run
Flood Zone: AFH
Marshall County, WV
HEC-RAS Version: RAS 6.6
Vertical Datum: NAVD88
Projection: NAD 1983 StatePlane West Virginia N FIPS 4701 (US Feet)
Terrain: 1-meter West Virginia FEMA R3 South Central (collected 2018-2019)
Land Use: 2024 NLCD
Hydrologic Method:
Duda et al., "Estimation of magnitude and frequency of floods for rural, unregulated streams in and near Virginia and West Virginia." September 8, 2025.
Additional Model Notes:
None
END DESCRIPTION:
DSS Export Rating Curves= 0
DSS Export Rating Curve Sorted= 0
DSS Export Volume Flow Curves= 0
DXF OffsetX= 0
DXF OffsetY= 0
DXF ScaleX= 0
DXF ScaleY= 0

--- MdleBwmRn.p01 (plan) ---

Plan Title=Floodplain
Program Version=6.60
Short Identifier=Floodplain
Geom File=g01
Flow File=f01
Subcritical Flow
K Sum by GR= 0
Std Step Tol= 0.01
Critical Tol= 0.01
Num of Std Step Trials= 20
Max Error Tol= 0.3
Flow Tol Ratio= 0.001
Split Flow NTrial= 30
Split Flow Tol= 0.02
Split Flow Ratio= 0.02
Log Output Level= 0
Friction Slope Method= 1
Unsteady Friction Slope Method= 2
Unsteady Bridges Friction Slope Method= 1
Parabolic Critical Depth
Global Vel Dist= 0 , 0 , 0
Global Log Level= 0
CheckData=False
Encroach Param=-1 ,0,0, 0
Flow Ratio Tolerance=0.1
Flow Ratio Min Ratio=0.5
Flow Ratio Max Ratio=4
Flow Ratio Max Iterations= 10
Mapping Interval=1HOUR
Computation Time Step Use Courant=        0
Computation Time Step Use Time Series=    0
Computation Time Step Count To Double=0
Computation Time Step Max Doubling=0
Computation Time Step Max Halving=0
Computation Time Step Residence Courant=0
Run HTab= 0
Run UNet= 0
Run Sediment= 0
Run PostProcess= 0
Run WQNet= 0
Run RASMapper=-1
UNET Theta= 0
UNET Theta Warmup= 0
UNET ZTol= 0
UNET ZSATol= 0
UNET MxIter= 0
UNET Max Iter WO Improvement= 0
UNET MaxInSteps= 0
UNET DtIC= 0
UNET DtMin= 0
UNET MaxCRTS= 0
UNET WFStab= 0
UNET SFStab= 0
UNET WFX= 1
UNET SFX= 1
UNET Gravity=32.17405
UNET 1D Methodology=Finite Difference
UNET DSS MLevel= 1
UNET Pardiso=0
UNET DZMax Abort= 0
UNET Use Existing IB Tables= 0
UNET Froude Reduction=False
UNET Froude Limit= 0
UNET Froude Power= 0
UNET D1 Cores= 0
UNET WindReference=Eulerian
UNET WindDragFormulation=Hsu (1988)
UNET D2 Coriolis=0
UNET D2 Cores= 0
UNET D2 Theta= 1
UNET D2 Theta Warmup= 1
UNET D2 Z Tol= 0.01
UNET D2 Volume Tol= 0.01
UNET D2 Max Iterations= 20
UNET D2 Advanced Convergence=0
UNET D2 WS Max Tol=0.15
UNET D2 WS RMS Tol=0.002
UNET D2 WS Stall Tol=1
UNET D2 Equation= 0
UNET D2 RampUpFraction=0.1
UNET D2 TimeSlices= 1
UNET D2 Turbulence Formulation=Non-Conservative (original)
UNET D2 Eddy Viscosity=0.3
UNET D2 Transverse Eddy Viscosity=0.1
UNET D2 Smagorinsky Mixing=0
UNET D2 BCVolumeCheck=0
UNET D2 Cores=0
UNET D2 SolverType=PARDISO (Direct)
UNET D2 Minimum Iterations= 3
UNET D2 Maximum Iterations= 30
UNET D2 Restart Number= 10
UNET D2 Relaxation Coeff=1.3
UNET D2 SOR Precondition Iterations= 10
UNET D2 ILUT Maximum Fill= 8
UNET D2 ILUT Tolerance=1E-08
UNET D2 Convergence Tolerance=0.00001
PS Theta= 1
PS WS Tol= 0.01
PS Volume Tol= 0.01
PS Max Iterations= 20
PS Equation= 0
PS Advance Time Step=-1
PS Target Courant=0.9
PS Time Slices= 1
PS Iterate With 2D=0
PS Project Initial WSE from DS=-1
PS Ramp Up Initial WSE from US=-1
PS Cores=0
UNET D1D2 MaxIter= 0
UNET D1D2 ZTol=0.01
UNET D1D2 QTol=0.1
UNET D1D2 MinQTol=1
Write IC File= 0
Write IC File at Fixed DateTime=0
Write IC File at Sim End=0
Echo Input=False
Echo Parameters=False
Echo Output=False
Write Detailed= 0
HDF Write Warmup=0
HDF Write Time Slices=0
HDF Flush=0
HDF Compression= 1
HDF Chunk Size= 1
HDF Spatial Parts= 1
HDF Use Max Rows=0
HDF Fixed Rows= 1
Calibration Method= 0
Calibration Iterations= 20
Calibration Max Change=0.05
Calibration Tolerance=0.2
Calibration Maximum=1.5
Calibration Minimum=0.5
Calibration Optimization Method= 1
WQ AD Non Conservative
WQ ULTIMATE=-1
WQ Max Comp Step=1HOUR
WQ Output Interval=15MIN
WQ Output Selected Increments= 0
WQ Create Restart=0
WQ Fixed Restart=0
WQ System Summary=0
WQ Write To DSS=0
Sorting and Armoring Iterations= 10
XS Update Threshold= 0.02
Bed Roughness Predictor= 0
Processes Affected by Predictor=Sediment Only
Hydraulics Update Threshold= 0.02
Energy Slope Method= 1
Volume Change Method= 1
Sediment Retention Method= 0
Sediment TS Multiplier= 1
Warm Up Method= 0
XS Weighting Method= 0
Number of US Weighted Cross Sections= 1
Number of DS Weighted Cross Sections= 1
Upstream XS Weight=0
Main XS Weight=1
Downstream XS Weight=0
Number of DS XS's Weighted with US Boundary= 1
Upstream Boundary Weight= 1
Weight of XSs Associated with US Boundary= 0
Number of US XS's Weighted with DS Boundary= 1
Downstream Boundary Weight= 0.5
Weight of XSs Associated with DS Boundary= 0.5
Percentile Method= 0
Sediment Output Level= 3
Mass or Volume Output= 0
Output Increment Type= 1
Profile and TS Output Increment= 1
Transport Output Increment 1
XS Output Flag= 0
XS Output Increment= 10
Read HDF5 Sediment Hotstart= 0
Sediment Hotstart Type= 0
Write Gradation File= 0
Read Gradation Hotstart= 0
Write HDF5 File= 1
Write Binary Output= 1
Write DSS Sediment File= 0
DSS Sediment Output Type= 1
SV Curve= 0
Specific Gage Flag= 0
Subcell Erosion Methods= 0
Subcell Deposition Methods= 0
Advection Scheme= 1
Matrix Solver= 0
Implicit Weighting Factor= 1
Maximum Outer Loop Convergence Iterations= 5
Convergence Maximum Absolute= 0.001
Convergence RMSE= 0.0001
Grain Fractions Max Abs Error= 0.001
Max Subgrid Regions= 1
Max Subgrid Length Scale= 3.402823E+38
Initial Layer Thickness= 3
Min Layer Thickness= 0.1
Max Layer Thickness= 6
Number of Layers= 5

--- MdleBwmRn.f01 (steady flow) ---

Flow Title=Flow
Program Version=6.60
Number of Profiles= 1
Profile Names=P100yr
River Rch & RM=MdleBwmRn,Main,9294
     826
River Rch & RM=MdleBwmRn,Main,4158
     919
Boundary for River Rch & Prof#=MdleBwmRn,Main            , 1
Up Type= 0
Dn Type= 3
Dn Slope=0.03966
DSS Import GetInterval= 0
DSS Import GetPeak= 0
DSS Import FillOption= 0

--- MdleBwmRn.g01 (geometry) ---

Geom Title=Geometry
Program Version=6.60

River Reach=MdleBwmRn       ,Main
Reach XY= 30
     1633235.648      472738.502     1633168.486      472617.609
     1633187.888      472442.987     1633032.669      472170.605
     1632769.242      472002.699     1632672.229      471778.823
     1632267.881      471588.768     1632235.404      471383.878
1632067.78482485471271.257570287     1631884.846      471305.551
     1631586.345      471152.719     1630688.934       471250.15
     1630573.833      471117.377     1630197.484 471003.07020438
     1629663.087      470904.7491629479.92633078470934.609267689
     1629432.005      470817.9411628647.13162337470614.879623367
     1628413.169      470412.439     1628046.849      470412.916
     1627911.211       470511.78     1627784.647      470391.902
     1627623.218      470451.602     1627494.743      470275.367
     1627361.493      470208.026      1626873.91      470165.803
     1626652.367      470378.018     1626458.808       470397.84
     1626150.776      470590.584     1625719.277      470418.057

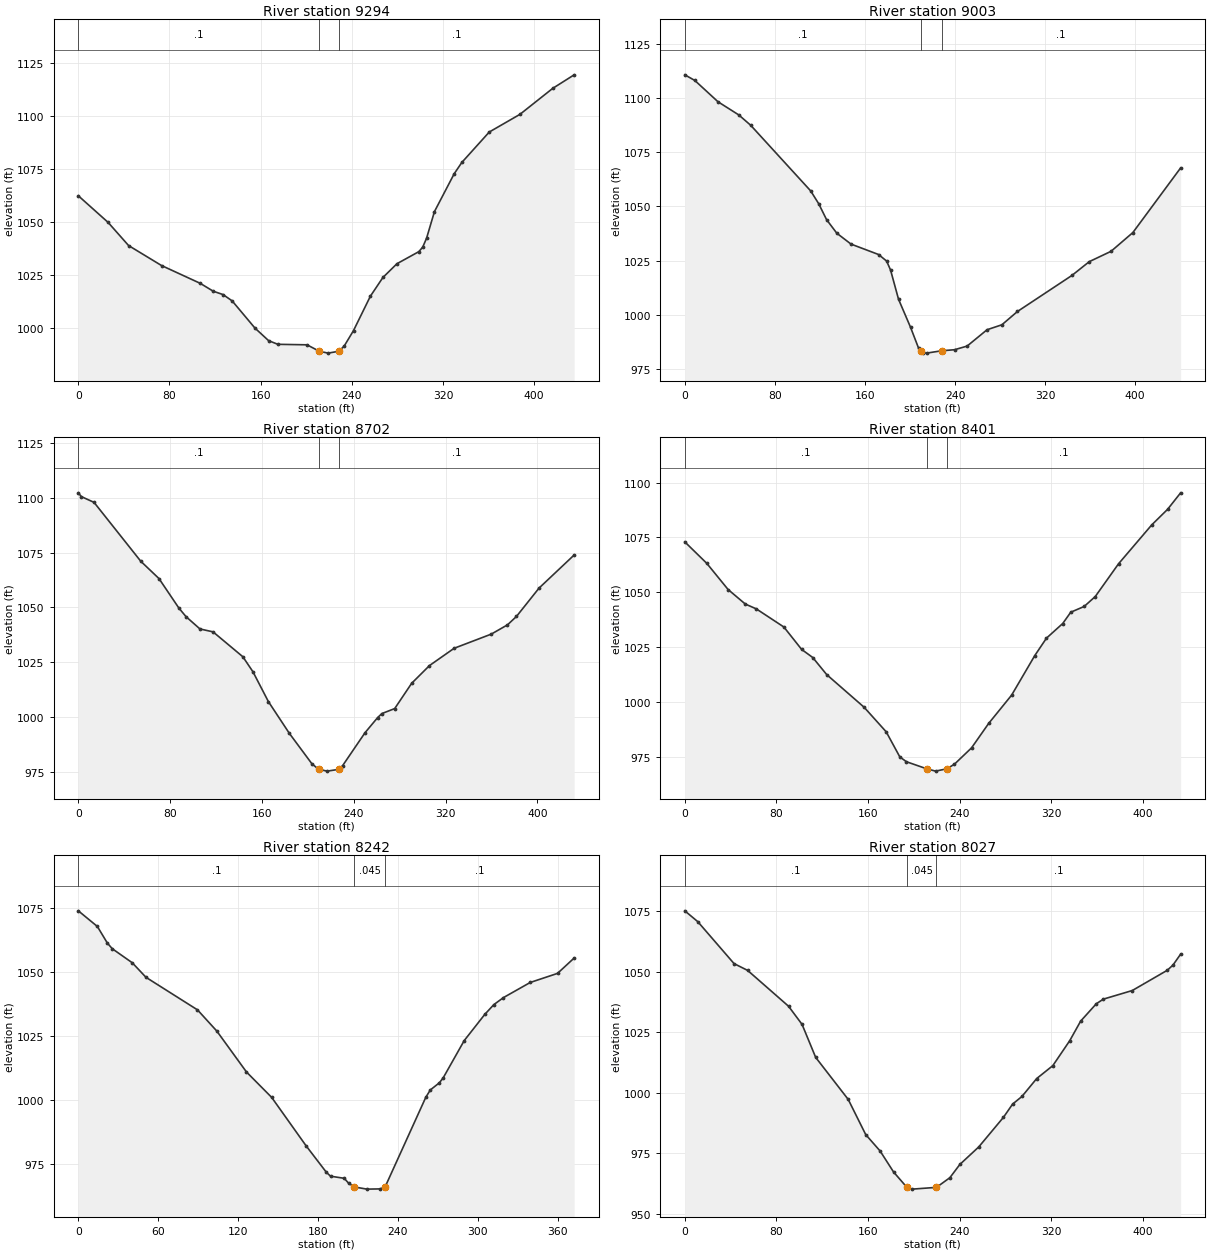
Type RM Length L Ch R = 1 ,9294    ,286.5,290.6,287.1
XS GIS Cut Line= 6
1633399.08838476472605.0422924161633315.50423434472643.572071001
1633251.04274909472688.5470466761633160.87298192472736.231006429
1633089.24320392472758.4612769191633005.67512959 472784.39593634
#Sta/Elev= 30
       0  1062.4    26.1 1049.89    44.1 1038.98      73 1029.58     107 1021.19
   118.4 1017.48     127 1015.91     135 1012.93     155 1000.13     167  994.21
   175.1   992.5   200.7  992.26  211.43989.2396   219.2  988.35  228.66989.2407
   233.3  991.68   241.5  998.99   256.3 1015.16   267.3 1023.97   279.6 1030.43
   298.8 1036.11   302.2 1038.23   305.6 1042.44   312.5 1054.96   329.8 1072.75
   336.5 1078.07   360.6 1092.41   387.5 1100.72   416.3 1112.96   435.1 1119.33
#Mann= 3 ,-1,0
       0      .1       0  211.43    .045       0  228.66      .1       0
Bank Sta=211.43,228.66
XS Rating Curve= 0 ,0
Exp/Cntr(USF)=0,0
Exp/Cntr=0.3,0.1

Type RM Length L Ch R = 1 ,9003    ,301,301.1,298.7
XS GIS Cut Line= 6
1633380.33710992472352.2524436711633299.42782292472385.567993835
1633230.07658367472414.124039084  1633137.609577472452.200078428
1633061.02180368472477.5894633381632969.16568817472509.170765013
#Sta/Elev= 30
       0 1110.79     8.9 1108.19    29.5 1098.34    47.9 1092.28    58.5  1087.5
   111.8 1057.17   118.9 1051.26   125.9  1043.9     135 1037.63   147.6 1032.61
   172.1 1027.79   179.2 1024.78   182.7 1020.66   189.8 1007.13   200.5  994.14
   207.6  984.53  209.36983.3405   211.1  982.42   214.7  982.25  228.08 983.338
   239.5  983.82   250.7   985.5   268.4  993.05   281.6  995.35   295.4 1001.48
   343.8 1018.14   359.2 1024.51   378.5 1029.27   397.9 1037.94   440.3 1067.79
#Mann= 3 ,-1,0
       0      .1       0  209.36    .045       0  228.08      .1       0
Bank Sta=209.36,228.08
XS Rating Curve= 0 ,0
Exp/Cntr(USF)=0,0
Exp/Cntr=0.3,0.1

Type RM Length L Ch R = 1 ,8702    ,302.7,301.3,292.4
XS GIS Cut Line= 6
1633226.81117025472084.2670872511633149.10922593472124.819827676
1633082.63790217472159.9263847621632993.03145409472204.507004261
 1632925.3285055472240.0266182571632847.83981533 472290.97960034
#Sta/Elev= 30
       0 1102.18     2.6 1100.47    13.7 1097.83    54.4 1071.03    70.3 1063.13
    87.6 1049.72    93.9 1045.77     106 1040.19   117.4 1038.87   143.4 1027.52
   152.2 1020.67   165.6 1007.14   183.9  992.65   203.5  978.83  209.43 976.251
   216.9  975.45  226.97976.2507   230.4  978.01   249.9  992.98   260.9  999.87
   264.6 1001.68   275.7 1003.93   290.5 1015.45     306 1023.51   327.5 1031.39
   359.9 1037.85     374 1042.06   381.8 1045.87   401.5  1058.8   432.1 1073.87
#Mann= 3 ,-1,0
       0      .1       0  209.43    .045       0  226.97      .1       0
Bank Sta=209.43,226.97
XS Rating Curve= 0 ,0
Exp/Cntr(USF)=0,0
Exp/Cntr=0.3,0.1

Type RM Length L Ch R = 1 ,8401    ,153.1,158.9,167.7
XS GIS Cut Line= 6
1632932.50106335471846.7865910831632868.53006268471915.216244251
1632824.08362925471975.9687474221632771.26188451 472061.01910226
1632726.94209126 472122.193848671632674.85262851472193.350858584
#Sta/Elev= 30
       0 1072.99    19.2 1063.19    37.8 1051.25    52.8 1044.63    62.4 1042.43
    86.5 1034.14     102 1023.92   111.7 1020.23   123.9 1012.42   156.5  997.56
   175.8  986.34   187.7  974.89   193.5  972.69  211.16969.4728   218.9  968.41
  228.83969.4734   235.4  971.59   250.3  979.02   265.2  990.14   285.3 1003.09
   305.5 1021.12   315.7 1029.07   329.9 1035.75   336.9  1040.9   348.6 1043.52
   358.3 1048.06   378.6 1062.98   407.6 1080.74   421.4 1087.82   432.8 1095.36
#Mann= 3 ,-1,0
       0      .1       0  211.16    .045       0  228.83      .1       0
Bank Sta=211.16,228.83
XS Rating Curve= 0 ,0
Exp/Cntr(USF)=0,0
Exp/Cntr=0.3,0.1

Type RM Length L Ch R = 1 ,8242    ,220.2,214.8,204.1
XS GIS Cut Line= 3
1632905.74230425471794.7902284671632742.44270234471883.438583786
1632562.81314025471933.983698661
#Sta/Elev= 30
       0 1073.88    14.3 1067.76    21.8 1061.27    25.5 1059.06    40.5 1053.58
    50.8 1047.89    89.5 1035.16     104 1026.88   126.3 1010.87   145.2 1000.95
   171.1  981.99   186.3  971.66   189.4  970.14   199.7  969.31   203.1  967.34
  207.31965.9316   216.7  965.08   226.9  965.17  230.47966.0061     261 1001.01
   264.4 1003.87   271.2 1006.66   274.1 1008.64   289.8 1023.13   305.3 1033.41
   312.1 1037.22   319.3 1039.96   339.4 1045.87   359.9 1049.42   372.4 1055.43
#Mann= 3 ,-1,0
       0      .1       0  207.31    .045       0  230.47      .1       0
Bank Sta=207.31,230.47
XS Rating Curve= 0 ,0
Exp/Cntr(USF)=0,0
Exp/Cntr=0.3,0.1

Type RM Length L Ch R = 1 ,8027    ,257.2,251.9,247.3
XS GIS Cut Line= 6
1632710.79302426471559.6008733841632661.66156085471632.004928055
1632619.54878419471694.065499473 1632558.7926721471774.017767388
1632503.54606343471828.2643780591632432.83098177471888.202578384
#Sta/Elev= 30
       0 1075.07    11.3 1070.62      43  1053.3    54.9 1050.48    90.6 1035.71
   102.4 1028.22   114.3  1014.6   142.7  997.27     158  982.75   170.6  975.96
   182.3  967.33     194  960.96   198.7  960.25   219.8  960.98   231.5  964.97
   240.2  970.43   256.7  977.66   278.2  989.83   286.3  995.35   294.4  998.47
   307.3 1005.87   321.4  1011.2   336.2 1021.52   345.7 1029.57   359.4 1036.74
   365.5 1038.63   390.8 1042.19   421.3 1050.53   426.3 1052.68     433 1057.19
#Mann= 3 ,-1,0
       0      .1       0     194    .045       0   219.8      .1       0
Bank Sta=194,219.8
XS Rating Curve= 0 ,0
Exp/Cntr(USF)=0,0
Exp/Cntr=0.3,0.1

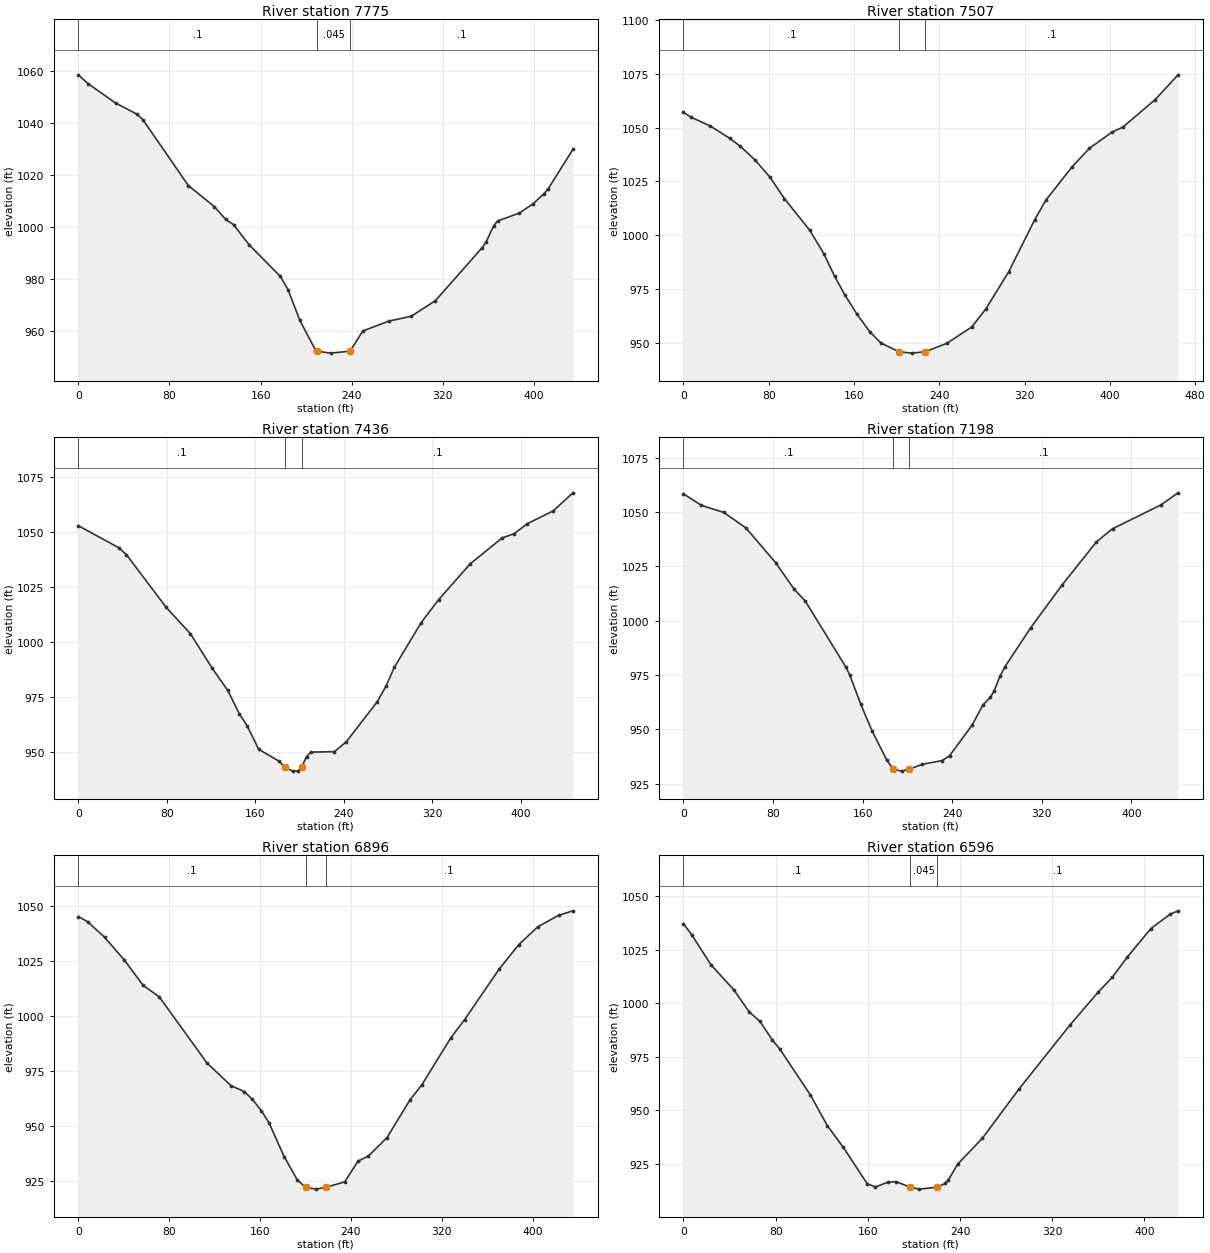
Type RM Length L Ch R = 1 ,7775    ,241.6,268.5,279.4
XS GIS Cut Line= 6
1632455.83475348 471439.733778371632394.56125398471514.387828541
 1632373.6456134471586.4175401151632346.76574589471682.737229374
1632326.60568122471754.9772423631632303.08571514471839.256601376
#Sta/Elev= 30
       0 1058.52     8.8 1055.05    32.8 1047.63    51.5 1043.37    56.8 1041.19
    96.6 1015.88   119.5 1007.75   129.4  1002.8   136.3 1000.81   149.9  993.09
   177.3  980.91   184.1  975.78   194.3  964.11   207.9  952.72   209.7  952.08
   221.5  951.33   238.6  952.09   249.7  959.86   272.6  963.66   292.3  965.55
   313.4  971.52   354.4  991.92   357.8  993.99   364.6 1000.42     368 1002.22
   387.1 1005.27   399.3 1008.92   408.9 1012.79   412.3 1014.53   434.1 1029.82
#Mann= 3 ,-1,0
       0      .1       0   209.7    .045       0   238.6      .1       0
Bank Sta=209.7,238.6
XS Rating Curve= 0 ,0
Exp/Cntr(USF)=0,0
Exp/Cntr=0.3,0.1

Type RM Length L Ch R = 1 ,7507    ,78.9,70.7,64.2
XS GIS Cut Line= 6
1632453.83568209471414.5709200951632365.67870617471449.286729917
1632290.99742509471441.4412731681632190.64001426471433.102707177
1632111.86130042471462.462884679 1632028.8539205471533.627440512
#Sta/Elev= 30
       0 1057.17     7.4  1054.8      25 1050.84    43.4 1045.07    53.2 1041.42
    67.3 1034.92    81.3 1026.91    94.7 1017.05   118.6 1002.23   131.8  991.33
   141.8  980.93   151.6  972.11   162.7  963.37   174.7  955.19   185.3  949.87
  202.32   945.8   214.2  945.16  226.71945.8013   247.1  949.71   270.5  957.32
   283.7  965.72   305.1  982.93   329.6 1007.26   340.1 1016.36   364.6 1031.79
   380.9 1040.41   402.2 1047.97   412.3 1050.27   442.6 1063.06     464 1074.57
#Mann= 3 ,-1,0
       0      .1       0  202.32    .045       0  226.71      .1       0
Bank Sta=202.32,226.71
XS Rating Curve= 0 ,0
Exp/Cntr(USF)=0,0
Exp/Cntr=0.3,0.1

Type RM Length L Ch R = 1 ,7436    ,245,238.3,228.6
XS GIS Cut Line= 3
1632362.83316549471244.5655366371632255.92900016471351.646009012
1632012.70606056471519.937834853
#Sta/Elev= 30
       0 1052.83    36.5 1042.82    43.5 1039.68    79.4 1015.68   101.4 1003.64
   121.1  987.93   135.1  977.87   145.6   967.2   152.6  961.79   163.1  951.06
   181.4  945.65   186.7  942.94   193.8  941.13   198.5  941.24  202.05  942.94
   206.3  947.76   210.3  949.78   231.5  949.97   242.2  954.43   270.1  972.61
   278.1  979.73   285.7  988.38     310 1008.74   325.8  1019.2   354.4 1035.52
   383.2 1047.26   394.2 1049.21   405.7 1053.66   429.4 1059.58   447.1 1067.77
#Mann= 3 ,-1,0
       0      .1       0   186.7    .045       0  202.05      .1       0
Bank Sta=186.7,202.05
XS Rating Curve= 0 ,0
Exp/Cntr(USF)=0,0
Exp/Cntr=0.3,0.1

Type RM Length L Ch R = 1 ,7198    ,287.2,301.4,304.8
XS GIS Cut Line= 6
1631997.10332784471080.5069556681632008.48978801471167.263015762
1632018.24993908471241.6253998431632031.26303643471340.774807841
1632032.17281151471416.2989350111631989.00951201471510.545465678
#Sta/Elev= 30
       0 1058.36    16.1 1053.02      36  1049.8    55.8 1042.65    82.3  1026.7
    98.8 1014.51   108.8 1009.01   145.2  978.48   148.5  975.01   158.4  961.49
   168.3  949.39   181.6  935.82  187.39 931.675   194.8  930.71  201.88931.6729
   213.5  933.87   231.2   935.6   237.8  937.89   257.7   951.8   267.5  961.19
   274.1  964.66   277.4  967.54   282.7  974.37   287.2  978.81   310.2  996.74
     338 1016.29   368.8 1036.21   383.2 1042.27   426.5 1053.25   441.7  1058.8
#Mann= 3 ,-1,0
       0      .1       0  187.39    .045       0  201.88      .1       0
Bank Sta=187.39,201.88
XS Rating Curve= 0 ,0
Exp/Cntr(USF)=0,0
Exp/Cntr=0.3,0.1

Type RM Length L Ch R = 1 ,6896    ,320.3,300.2,295
XS GIS Cut Line= 6
 1631907.0552796471070.9364367571631855.72106467471144.535370916
1631796.51941143471190.5805544261631717.80598618   471252.259893
1631664.42125042471307.533732593 1631618.5145181471389.322282925
#Sta/Elev= 30
       0 1045.16     8.2 1042.81    23.1 1035.79    40.6 1025.41    57.1 1013.91
    71.2  1008.8   113.4  978.67   134.5  968.44   146.2  965.75   153.2   962.3
   161.1  957.16   167.8  951.72   181.2  936.31   192.8  925.71  200.19922.3465
   209.3  921.54   217.7922.3463   234.5  924.82   246.2   934.2   255.4  936.57
   271.7  944.87   291.9  961.91   302.5  968.88     328  990.19   340.1  998.43
   370.4 1021.25   387.7 1032.38   404.6 1040.55   423.1 1045.75   435.4 1047.74
#Mann= 3 ,-1,0
       0      .1       0  200.19    .045       0   217.7      .1       0
Bank Sta=200.19,217.7
XS Rating Curve= 0 ,0
Exp/Cntr(USF)=0,0
Exp/Cntr=0.3,0.1

Type RM Length L Ch R = 1 ,6596    ,292.3,299.7,300.8
XS GIS Cut Line= 6
1631423.51293959470977.7030274271631437.64709768471066.876733586
1631461.41673517 471138.352640511631500.80904484471230.266826749
1631530.35262093471299.2030405851631551.48053142471385.156936929
#Sta/Elev= 30
       0 1037.05     7.3 1031.82    23.9 1017.87    43.9 1006.07    57.1  995.87
    66.4  991.47    77.1   982.8    83.7  978.48   110.2   957.1   124.9  942.74
   138.8  932.61   159.5  915.68   166.5  914.19   177.1  916.36   184.3  916.69
  196.69914.1112   204.7  913.18  220.42914.1103   227.1  915.84   229.7  917.31
   237.8  924.77   259.3  936.88   291.4  960.09   335.5  989.86   359.6 1004.98
   372.1 1012.04   385.2 1021.53   405.5 1034.76   422.4 1041.54   429.1 1043.05
#Mann= 3 ,-1,0
       0      .1       0  196.69    .045       0  220.42      .1       0
Bank Sta=196.69,220.42
XS Rating Curve= 0 ,0
Exp/Cntr(USF)=0,0
Exp/Cntr=0.3,0.1

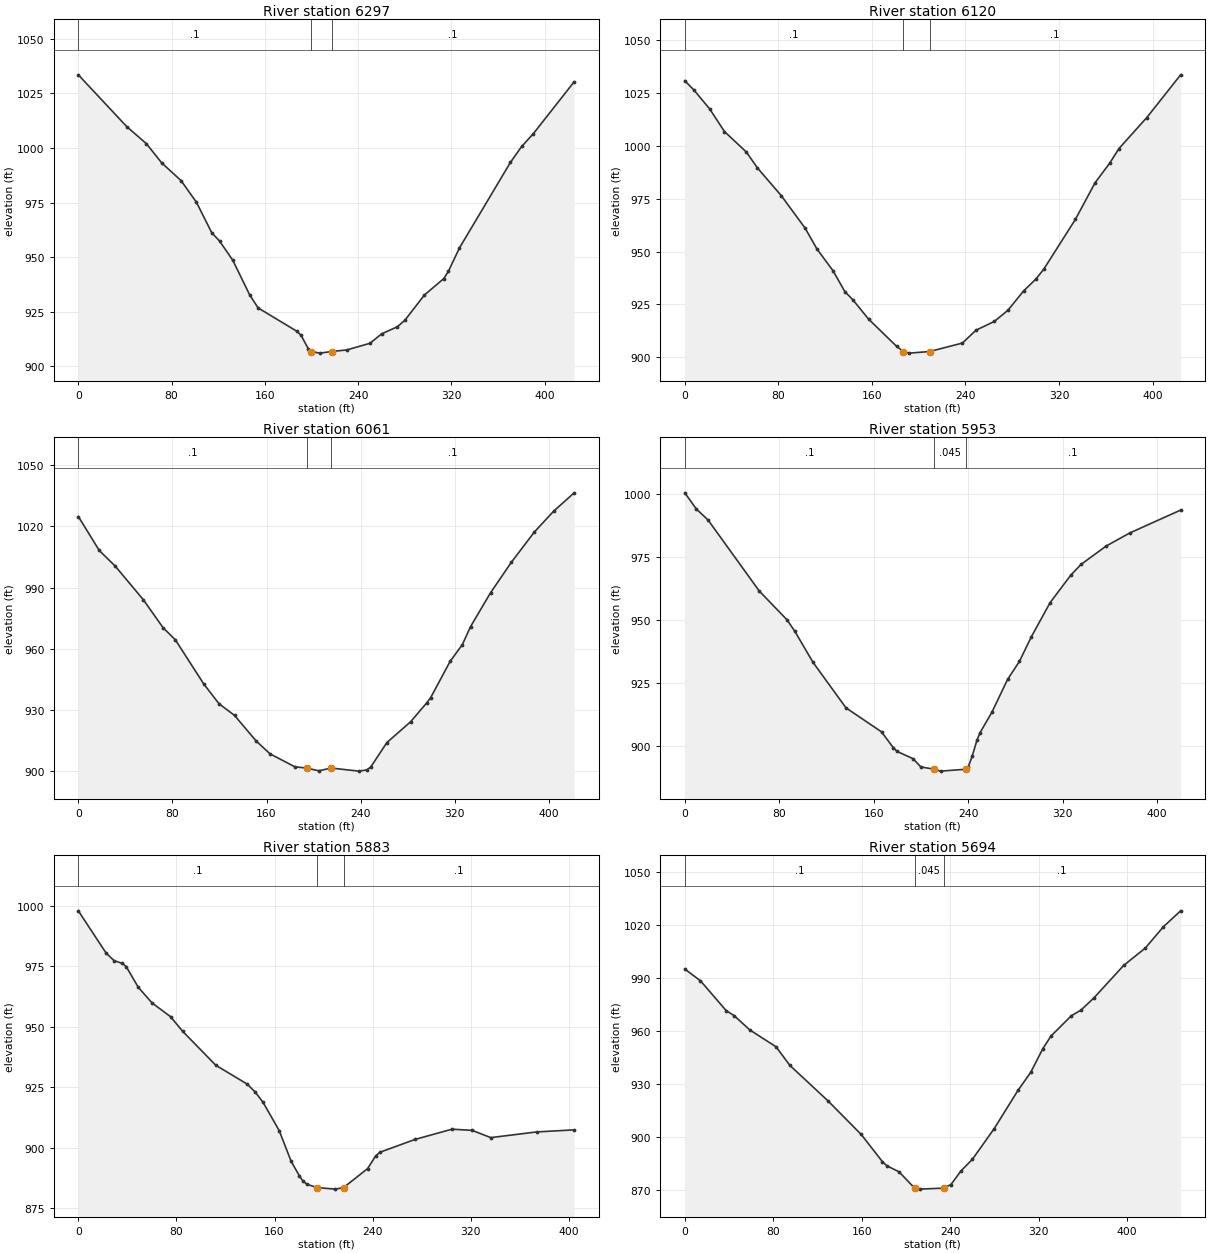
Type RM Length L Ch R = 1 ,6297    ,179,177,176.1
XS GIS Cut Line= 6
1631162.36418368470966.4615800831631173.49145801471053.251432762
1631183.02884051471127.6423600911631196.26109751471226.764537171
1631209.90837993471300.6285626741631226.94279468471386.660870925
#Sta/Elev= 30
       0 1033.44    41.6  1009.7    58.3 1001.98    71.5  993.16    88.1  985.03
   101.3  975.14   114.5  961.13   121.2  957.34   132.5  948.55   147.1  932.62
   154.2  926.77   187.3  916.13     191  914.29   197.3  908.02  199.54 906.816
   207.2  906.08  217.22906.8167   230.4  907.56   250.2  910.59   260.1  914.89
   273.5   918.1   280.1  921.12   296.8  932.64   313.5  940.21   317.4   943.5
   326.9  954.21   370.6  993.34   380.3 1000.67   390.4 1006.58   425.3 1030.27
#Mann= 3 ,-1,0
       0      .1       0  199.54    .045       0  217.22      .1       0
Bank Sta=199.54,217.22
XS Rating Curve= 0 ,0
Exp/Cntr(USF)=0,0
Exp/Cntr=0.3,0.1

Type RM Length L Ch R = 1 ,6120    ,58.7,58.6,58.7
XS GIS Cut Line= 2
1630962.75846452471003.6644274811631072.98569581471413.079857967
#Sta/Elev= 30
       0 1030.84     7.8 1026.48    21.4 1017.42    33.9 1006.82    52.7  997.08
    62.1  989.58    82.5  976.45   102.9  961.06   113.1  951.11   126.7  940.94
   136.9  930.98   143.7  927.16   157.1  918.02   181.1  905.12  187.01902.6134
   191.9  901.88  209.27902.6282   237.4  906.65     249  912.74   264.6  916.86
   276.2  922.11   289.8  931.37     300  936.83   306.8  941.48     334  965.21
   350.9  982.61   363.2  991.72   371.3  998.77   395.1 1013.45     424 1033.66
#Mann= 3 ,-1,0
       0      .1       0  187.01    .045       0  209.27      .1       0
Bank Sta=187.01,209.27
XS Rating Curve= 0 ,0
Exp/Cntr(USF)=0,0
Exp/Cntr=0.3,0.1

Type RM Length L Ch R = 1 ,6061    ,107.2,107.7,109.7
XS GIS Cut Line= 2
1630906.70004404471016.8916952341631014.40779575471424.417516043
#Sta/Elev= 30
       0 1024.83    17.8 1008.19    31.4 1000.51    55.2   984.1    72.1  970.32
    82.5  964.41   106.6  942.83   119.6  933.12   132.8   927.4   151.2  914.85
     163  908.56   184.1  902.22   194.1  901.61   204.5  900.26   214.7  901.63
   238.4  900.11   245.2   900.7   248.6  902.15   262.3   914.1   282.5  924.31
   296.1  933.49   299.5  936.09     316  953.82   326.5  962.13   333.4  970.87
   350.4  987.47     368 1002.32   387.7 1017.26   404.1 1027.46   421.5 1036.43
#Mann= 3 ,-1,0
       0      .1       0   194.1    .045       0   214.7      .1       0
Bank Sta=194.1,214.7
XS Rating Curve= 0 ,0
Exp/Cntr(USF)=0,0
Exp/Cntr=0.3,0.1

Type RM Length L Ch R = 1 ,5953    ,69,70.1,75.1
XS GIS Cut Line= 2
1630816.26560241471031.1323825121630892.95024145471443.985687076
#Sta/Elev= 30
       0 1000.56     9.7  994.17    19.7  989.77    63.1  961.53    86.5  950.15
    93.2  945.54   108.5  933.28   136.5  915.15   166.6  905.61   176.6  899.29
   179.9  897.81   193.3  894.95   199.9  891.68  211.27890.7682   216.6  890.01
   237.8 890.751     240  891.62   243.3  895.83   247.5  902.41     250  905.26
     260  913.34   273.4  926.47   283.4  933.61   293.4  943.31   309.4  956.96
   326.7  967.74   335.5  972.11   356.8  979.41   376.8  984.61   419.9   993.7
#Mann= 3 ,-1,0
       0      .1       0  211.27    .045       0   237.8      .1       0
Bank Sta=211.27,237.8
XS Rating Curve= 0 ,0
Exp/Cntr(USF)=0,0
Exp/Cntr=0.3,0.1

Type RM Length L Ch R = 1 ,5883    ,167.9,188.8,195.5
XS GIS Cut Line= 2
1630788.81621998471034.429409765 1630784.9407734471438.767669527
#Sta/Elev= 30
       0  998.01    22.7  980.51    29.2   977.4    35.8  976.32    39.1  974.93
    48.9   966.4    60.1  959.95    75.2  954.26      85  948.26   112.1  934.18
   137.5  926.46   144.1  923.21   150.6   918.9   163.8   907.2   173.6  894.44
   180.2  888.55   183.4  886.14   186.7  884.93   194.8883.6013   209.7  882.97
   216.3  883.61   235.9  891.44   242.5  896.66   245.8  898.18   274.6  903.51
   304.8  907.75   321.2  907.26   336.4  904.26   373.7  906.61   404.4  907.47
#Mann= 3 ,-1,0
       0      .1       0   194.8    .045       0   216.3      .1       0
Bank Sta=194.8,216.3
XS Rating Curve= 0 ,0
Exp/Cntr(USF)=0,0
Exp/Cntr=0.3,0.1

Type RM Length L Ch R = 1 ,5694    ,314.2,294.3,286.5
XS GIS Cut Line= 6
1630768.24554934471029.4630945031630715.27321434471112.626970172
1630658.59222534471175.0169372561630570.61274251471223.368218511
1630503.45605268471256.8307500031630437.68715534471318.463828832
#Sta/Elev= 30
       0   995.2    14.2  988.52    37.4  971.67    44.7  968.75    58.8  960.71
    82.6  951.12      95  940.65   129.4  920.59   159.6  901.47   178.7  886.14
   182.9  883.69   193.8  880.33  207.85  871.09   212.5  870.52   234.1871.0897
   240.8  873.14   249.9  880.91   260.1  887.38   279.9  904.82   301.4  926.49
   312.9  936.67   323.9  950.13   331.2  957.21   349.6  968.71   358.3  971.91
   370.1  978.87     397  997.25   416.5 1007.04     433  1019.2   448.5 1028.17
#Mann= 3 ,-1,0
       0      .1       0  207.85    .045       0   234.1      .1       0
Bank Sta=207.85,234.1
XS Rating Curve= 0 ,0
Exp/Cntr(USF)=0,0
Exp/Cntr=0.3,0.1

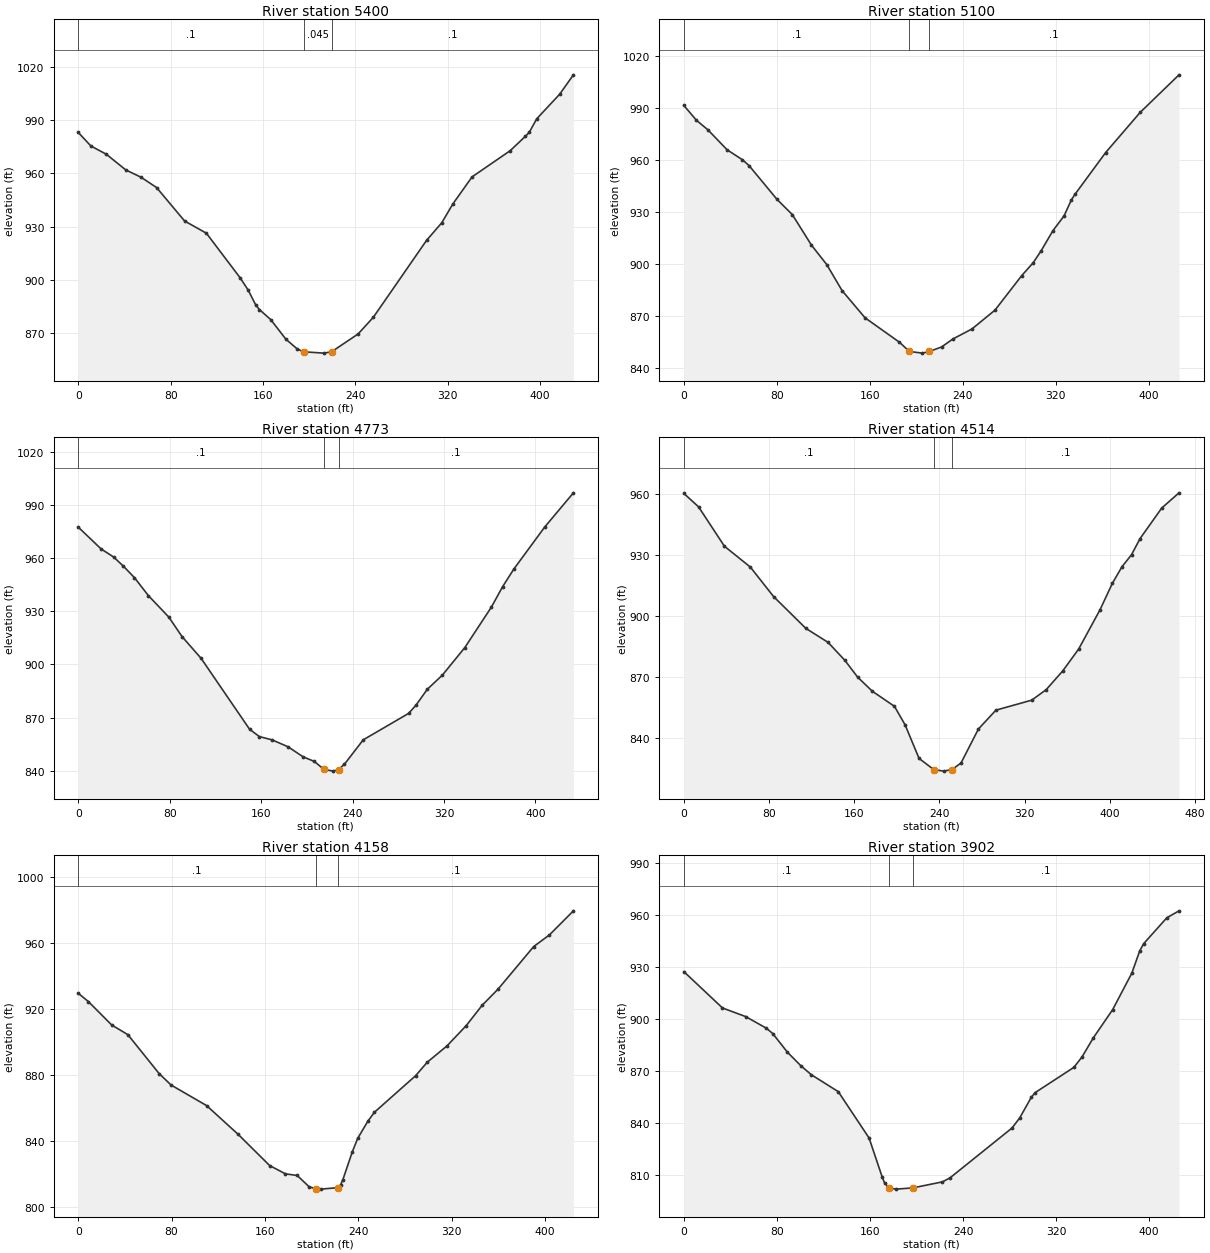
Type RM Length L Ch R = 1 ,5400    ,290.8,299.6,297
XS GIS Cut Line= 6
1630390.62163268470865.9562036691630372.59082884470954.608913511
1630374.21746601471029.7773983331630381.70301534471129.511450842
1630388.59703043471204.1940442621630380.25780825471292.145640001
#Sta/Elev= 30
       0  982.97    10.9  975.37    24.3  970.72    41.1  961.93    54.5  957.75
    67.8  952.02    92.1  933.22     111  926.34   140.3  901.22   147.1  894.47
   153.6  886.21   156.9  883.45   166.7  877.82   179.9  866.77   189.8  861.26
  195.32859.7029   212.8  858.96  219.41859.7037   242.4  869.71   255.6  879.08
   301.7  922.28   314.9   932.2   324.7  942.96   341.2  958.01   374.2  972.72
   387.4  980.82   390.7  983.01   397.2  990.64     417  1004.4     429 1015.35
#Mann= 3 ,-1,0
       0      .1       0  195.32    .045       0  219.41      .1       0
Bank Sta=195.32,219.41
XS Rating Curve= 0 ,0
Exp/Cntr(USF)=0,0
Exp/Cntr=0.3,0.1

Type RM Length L Ch R = 1 ,5100    ,325.7,327,326.5
XS GIS Cut Line= 6
1630125.69302867470790.4261710051630116.62710193 470877.85414575
1630109.63794267 470952.928798751630103.59103876471052.938441262
1630101.13828775471127.8661129181630093.94046751471215.134311095
#Sta/Elev= 30
       0  991.39    10.8  982.86    20.7  977.34    37.2  965.83    50.4  960.07
    56.1   956.7    80.1  937.25    93.3  928.46   109.8   910.8   122.9  899.66
   136.1  884.62   155.9   868.9   185.5  854.81     194849.5148   205.2  848.54
  211.28 849.516   221.7  852.08   231.5  856.72   247.9   862.5   267.7  873.36
   290.6   893.2   300.5  900.65   307.1  907.26   317.5  919.16   327.1  927.69
   333.3   936.8   336.6  940.25   362.9  964.25   392.6  987.41     426 1009.07
#Mann= 3 ,-1,0
       0      .1       0     194    .045       0  211.28      .1       0
Bank Sta=194,211.28
XS Rating Curve= 0 ,0
Exp/Cntr(USF)=0,0
Exp/Cntr=0.3,0.1

Type RM Length L Ch R = 1 ,4773    ,259.1,259.4,258.2
XS GIS Cut Line= 3
1629879.75518843470734.0325173971629801.78470777470895.194844791
1629780.07362327471148.457446114
#Sta/Elev= 30
       0  977.48      20  965.17    30.9  960.64    39.3  955.57    49.1  949.02
    61.4   938.8    79.2  926.74    90.8   915.7   107.4   903.5   149.8   863.5
   158.4   859.3   169.6  857.45   183.5  853.54   196.7  847.88   206.5  845.29
  214.89840.7808     223  839.81  227.75840.7268   232.9  843.75   249.3  857.47
   288.9  872.35   295.4  876.96   305.3  885.97   318.5  893.96   338.2  909.56
   361.3  932.24   371.2  943.86   381.1  953.87   408.1  977.59   433.2  996.86
#Mann= 3 ,-1,0
       0      .1       0  214.89    .045       0  227.75      .1       0
Bank Sta=214.89,227.75
XS Rating Curve= 0 ,0
Exp/Cntr(USF)=0,0
Exp/Cntr=0.3,0.1

Type RM Length L Ch R = 1 ,4514    ,354.1,356.3,358.7
XS GIS Cut Line= 6
1629614.65632109470702.9027240131629580.59700601470800.585927591
1629549.80999409470889.6218387481629547.59280692470994.325697586
1629566.62098409471066.8718123441629588.82074285471151.508782178
#Sta/Elev= 30
       0  960.48    13.8  953.88    38.1  934.49    62.4  924.25    84.2  909.76
   114.5   894.1   135.4  887.19   151.2  878.33   163.1  870.12     177  863.13
   197.7  855.74   207.7  846.63   220.8  830.12  234.56 824.618   243.8  823.84
  251.84824.6173   260.2  827.83   276.6  844.59     293  853.84   326.6  858.76
   340.2  863.93   355.8  873.19   370.7  883.93   390.7   903.2   402.4  916.32
   411.4  924.45   420.3  930.31   428.3  938.23   448.7   953.3   464.9  960.78
#Mann= 3 ,-1,0
       0      .1       0  234.56    .045       0  251.84      .1       0
Bank Sta=234.56,251.84
XS Rating Curve= 0 ,0
Exp/Cntr(USF)=0,0
Exp/Cntr=0.3,0.1

Type RM Length L Ch R = 1 ,4158    ,255.9,256.1,254.1
XS GIS Cut Line= 2
1629339.92016558470592.6078068351629239.17005593471004.941765672
#Sta/Elev= 30
       0  929.34     8.7  924.29    28.6  910.14    42.5  904.24    69.3  880.64
    79.6  873.67     110  861.22   137.1  843.73   164.1  824.81   177.6  819.81
   187.7  818.81   197.9  811.96203.4267810.8384   207.8  810.54222.3989811.4184
   224.9  813.16   226.8  816.22     235  833.32   239.6   841.4   248.3   851.8
   253.9  857.18   289.2  879.35   299.2  887.55   316.1  897.43   332.6  909.75
   346.2  922.03     360  931.96   390.4  957.67   403.9  964.75   424.5  979.37
#Mann= 3 ,-1,0
       0      .1       0203.4267    .045       0222.3989      .1       0
Bank Sta=203.4267,222.3989
XS Rating Curve= 0 ,0
Exp/Cntr(USF)=0,0
Exp/Cntr=0.3,0.1

Type RM Length L Ch R = 1 ,3902    ,306.1,306.8,302
XS GIS Cut Line= 6
1629081.22202051470528.9473632571629067.19022442470615.725733012
 1629056.9192476470690.1924475881629041.54329409470789.086606756
 1629029.3307201470863.057259336 1629015.0843575470949.348425344
#Sta/Elev= 30
       0   927.2    33.2  906.23    53.1  901.27    70.9  894.57    76.4  891.46
      89  880.73   100.6  872.87   109.6   867.7   132.7  857.97   159.2  831.21
   170.4  808.83   172.5  805.37  176.01802.4425   182.5  801.72   196.9802.4412
   222.3  805.92   228.9  808.29   282.1     837   288.7  842.83   298.7  854.77
     302  857.43   335.3     872   342.3  878.05   351.9  888.95   368.6  905.31
   385.1   926.4   391.8  939.11   395.2  943.33   415.1  958.24   425.6  962.28
#Mann= 3 ,-1,0
       0      .1       0  176.01    .045       0   196.9      .1       0
Bank Sta=176.01,196.9
XS Rating Curve= 0 ,0
Exp/Cntr(USF)=0,0
Exp/Cntr=0.3,0.1

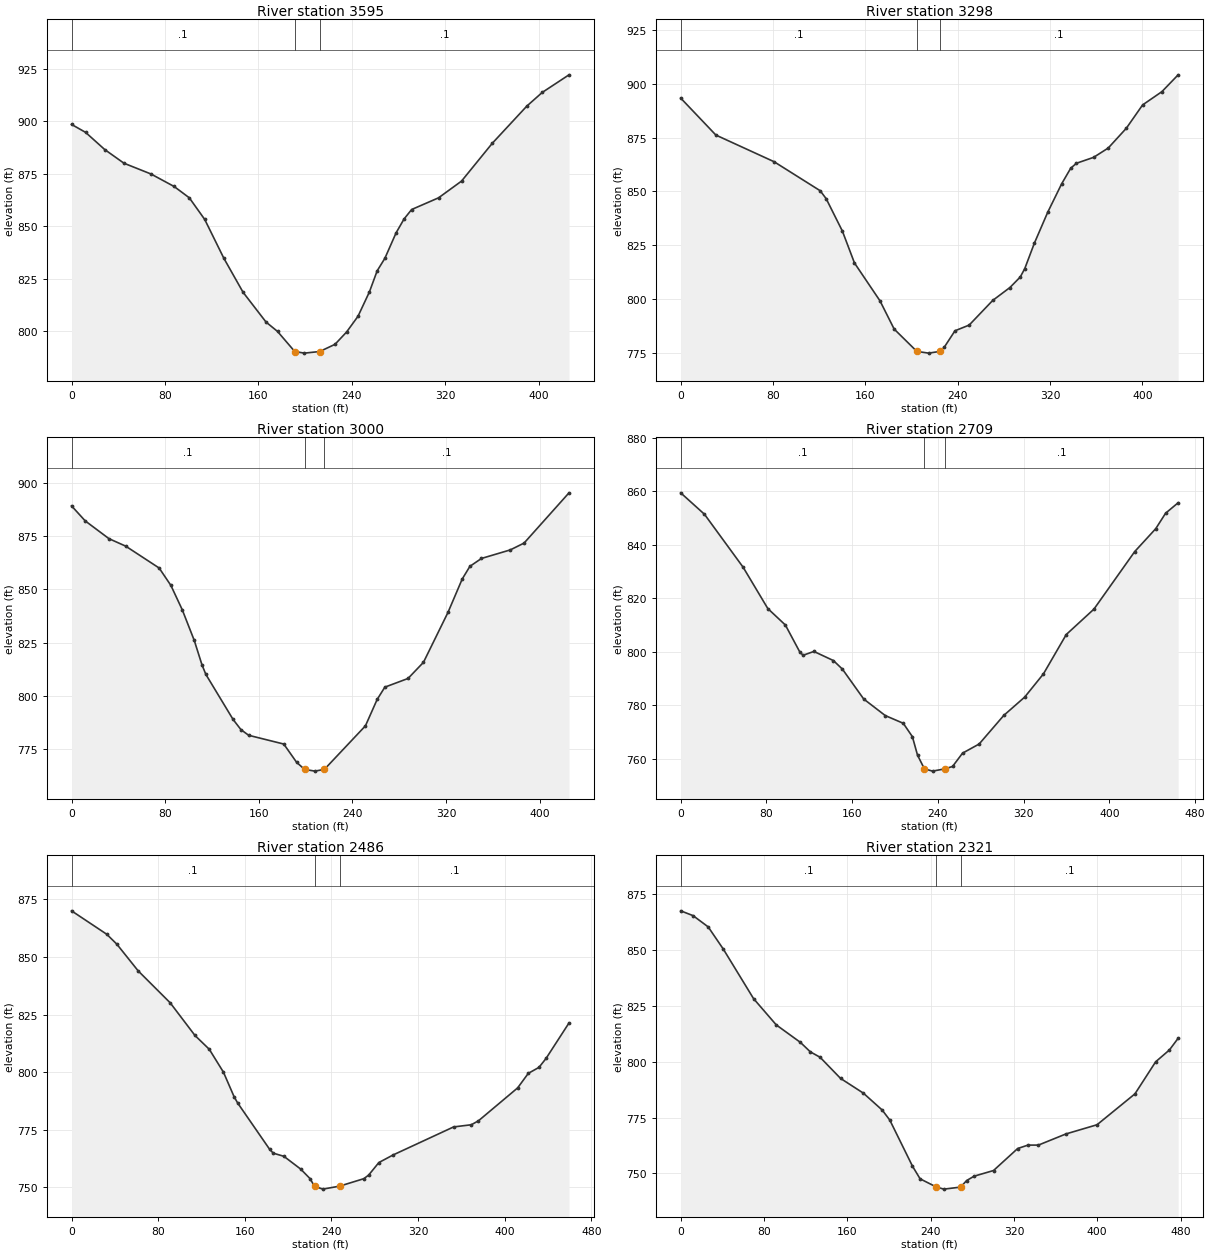
Type RM Length L Ch R = 1 ,3595    ,288.9,296.6,307.5
XS GIS Cut Line= 6
1628780.01133683 470428.371120841628772.76233558470515.881444499
1628773.93424925470590.8724362551628775.49658209 470690.86009717
1628775.80530851 470765.864212261628768.34272501470853.491661668
#Sta/Elev= 30
       0  898.59      12  894.81    28.4  886.62    44.9   880.1      68  874.98
    87.8  869.03   100.8  863.64     114  853.33   130.4  834.82   146.8  818.67
   166.5  804.46   176.3  800.02  191.06790.4412   199.3  789.68  212.42790.4431
   225.5  793.87   235.4  799.72   245.2  807.23     255  818.88   261.6  828.87
   268.2  834.84   277.8  846.96   284.6  853.55   291.1  858.06   314.1  863.62
   333.8  871.59   360.1  889.58   389.7  907.31   402.9  913.82   425.8   922.2
#Mann= 3 ,-1,0
       0      .1       0  191.06    .045       0  212.42      .1       0
Bank Sta=191.06,212.42
XS Rating Curve= 0 ,0
Exp/Cntr(USF)=0,0
Exp/Cntr=0.3,0.1

Type RM Length L Ch R = 1 ,3298    ,308.7,298.4,288.8
XS GIS Cut Line= 6
1628695.10796334470365.9148809161628627.59792776470421.580780089
1628569.73222984470469.293939263 1628490.2153285 470530.04611434
1628427.45659576470573.0374981761628369.25756517470644.856252179
#Sta/Elev= 30
       0  893.47    30.5  876.26    80.9  863.87   120.9  850.35   126.1  846.64
   140.1  831.61   150.6  816.74   172.7  799.13     185  785.98  204.69 775.579
   214.9  774.79  224.51775.5802   228.3  777.45   237.7  785.19     250  787.84
   270.4  799.31   285.3  805.31   294.3  810.23   298.2  814.15   306.5  825.96
   318.1  840.38   330.1  853.53     338  860.84     343  863.15   357.8  865.88
   370.5  870.22   386.2  879.44   400.3  890.29     417  896.45   431.1  904.29
#Mann= 3 ,-1,0
       0      .1       0  204.69    .045       0  224.51      .1       0
Bank Sta=204.69,224.51
XS Rating Curve= 0 ,0
Exp/Cntr(USF)=0,0
Exp/Cntr=0.3,0.1

Type RM Length L Ch R = 1 ,3000    ,299.4,290.8,286.8
XS GIS Cut Line= 6
1628228.67385684470208.9857328391628243.29554676470295.255245343
1628255.82833008470369.2006355081628271.94509576470467.895319998
1628281.21246567 470542.394186751628291.23213068470629.443881422
#Sta/Elev= 30
       0  889.09    11.7  882.05      32  873.73    46.3  870.23    74.9  859.98
    84.9  851.85    94.6  840.48   104.9  826.06   111.5  814.64   114.8  810.17
   138.1  789.05   144.8   784.3   151.4  781.65   181.4  777.55   192.4  768.98
   199.2765.6873     208  764.87  216.11765.6859   251.2  786.08   261.2  798.42
   267.8   804.2   287.6  808.26   300.8  815.82   321.8  839.25   333.9  854.81
   340.5  860.78   350.4  864.47     375  868.47   386.8  871.67   425.2   895.2
#Mann= 3 ,-1,0
       0      .1       0   199.2    .045       0  216.11      .1       0
Bank Sta=199.2,216.11
XS Rating Curve= 0 ,0
Exp/Cntr(USF)=0,0
Exp/Cntr=0.3,0.1

Type RM Length L Ch R = 1 ,2709    ,199.1,223.1,235.9
XS GIS Cut Line= 6
1627938.55435833470234.3843040911627940.37292425470335.375571921
1627955.74592501470423.9728356751628034.67358868470489.102298588
1628076.59771742470555.2005915941628110.94246501 470641.29917267
#Sta/Elev= 30
       0  859.49    22.2  851.47    58.3  831.64    81.3  816.21    97.7  810.05
   111.3  799.85   114.3  798.75   124.3  800.17   142.5  796.76   150.9  793.56
   170.8  782.37   190.9  776.19   207.7   773.3   216.2   768.3     221  761.38
  227.41756.2706     235  755.41  246.71756.2709   253.7  757.16     263  762.13
   278.5  765.55   301.5  776.25     321   783.1   338.5  791.78   359.8   806.5
   385.6  815.99   423.7  837.53   443.3  846.09   452.5  851.87   464.2  855.78
#Mann= 3 ,-1,0
       0      .1       0  227.41    .045       0  246.71      .1       0
Bank Sta=227.41,246.71
XS Rating Curve= 0 ,0
Exp/Cntr(USF)=0,0
Exp/Cntr=0.3,0.1

Type RM Length L Ch R = 1 ,2486    ,178.5,164.9,146.5
XS GIS Cut Line= 4
 1627868.4725862470214.7853410311627862.17388727470411.444718754
1627801.98631971470460.4345993261627791.48848816470645.196434624
#Sta/Elev= 30
       0  870.07    32.5   859.9    41.8  855.61    61.5  844.01    91.1  830.12
     114  815.93   127.2  809.94   140.3  799.98   150.1  789.35   153.4  786.62
     183  766.45   186.3  764.82   196.1  763.45   211.6  757.91   220.2  753.79
   224.4  750.43   232.1   749.2  247.59750.5027   269.9  753.73   274.4  755.31
   283.8  760.74   296.9  764.03   352.8  776.21   369.2  777.16   375.8  778.88
     412  793.18   421.8  799.48   431.7  802.09   438.2  805.96   459.4  821.37
#Mann= 3 ,-1,0
       0      .1       0   224.4    .045       0  247.59      .1       0
Bank Sta=224.4,247.59
XS Rating Curve= 0 ,0
Exp/Cntr(USF)=0,0
Exp/Cntr=0.3,0.1

Type RM Length L Ch R = 1 ,2321    ,269.2,290.8,301.4
XS GIS Cut Line= 4
1627778.52645723470193.345761739 1627680.8273465470398.910307882
 1627714.3224277470461.3304142851627739.05810284470638.913698081
#Sta/Elev= 30
       0  867.67    11.9  865.51    26.4  860.47      41  850.46      70  828.29
    91.8  816.52     115  808.68   124.5  804.44   133.8  802.04   153.5  792.55
   175.4  785.94   193.5  778.36   200.8  773.86   222.6  753.18   229.9  747.52
   245.4  743.87   252.7   742.9268.7861 743.806   274.6  746.75   281.8  748.71
   300.4  751.24   323.6  761.11   333.5  762.64   343.5  762.64     370  767.65
   399.8  771.76   436.2  785.61   456.1  799.99   469.3  805.29   477.7  810.54
#Mann= 3 ,-1,0
       0      .1       0   245.4    .045       0268.7861      .1       0
Bank Sta=245.4,268.7861
XS Rating Curve= 0 ,0
Exp/Cntr(USF)=0,0
Exp/Cntr=0.3,0.1