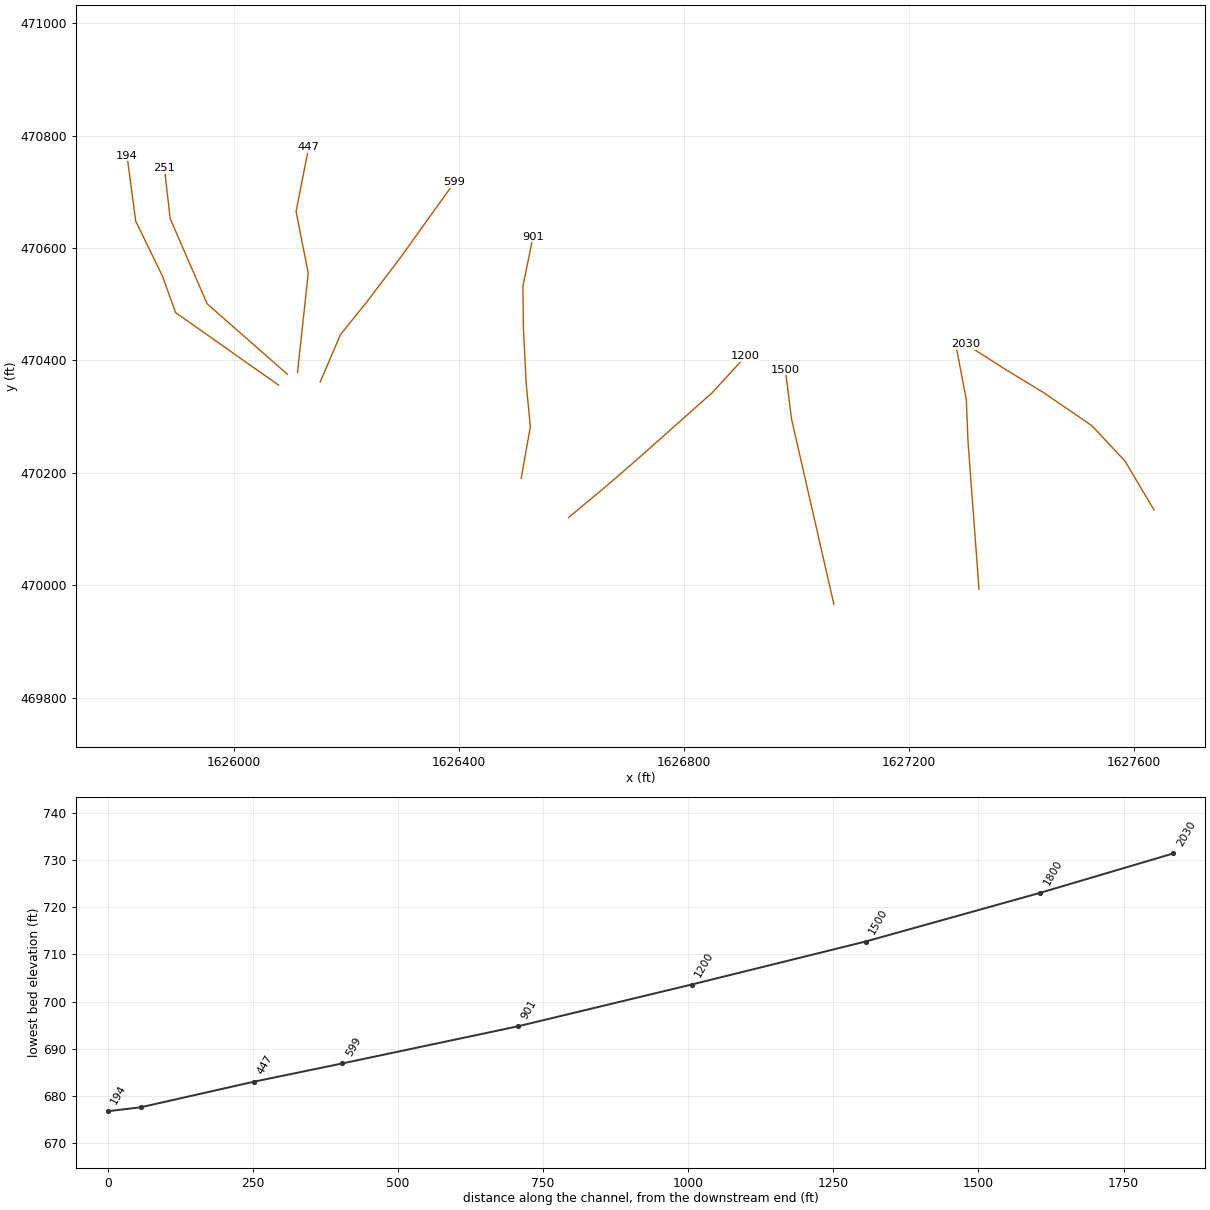
HEC-RAS study MdleBwmRn.prj: MdleBwmRn

--- MdleBwmRn.g01 (geometry) --- (continued)

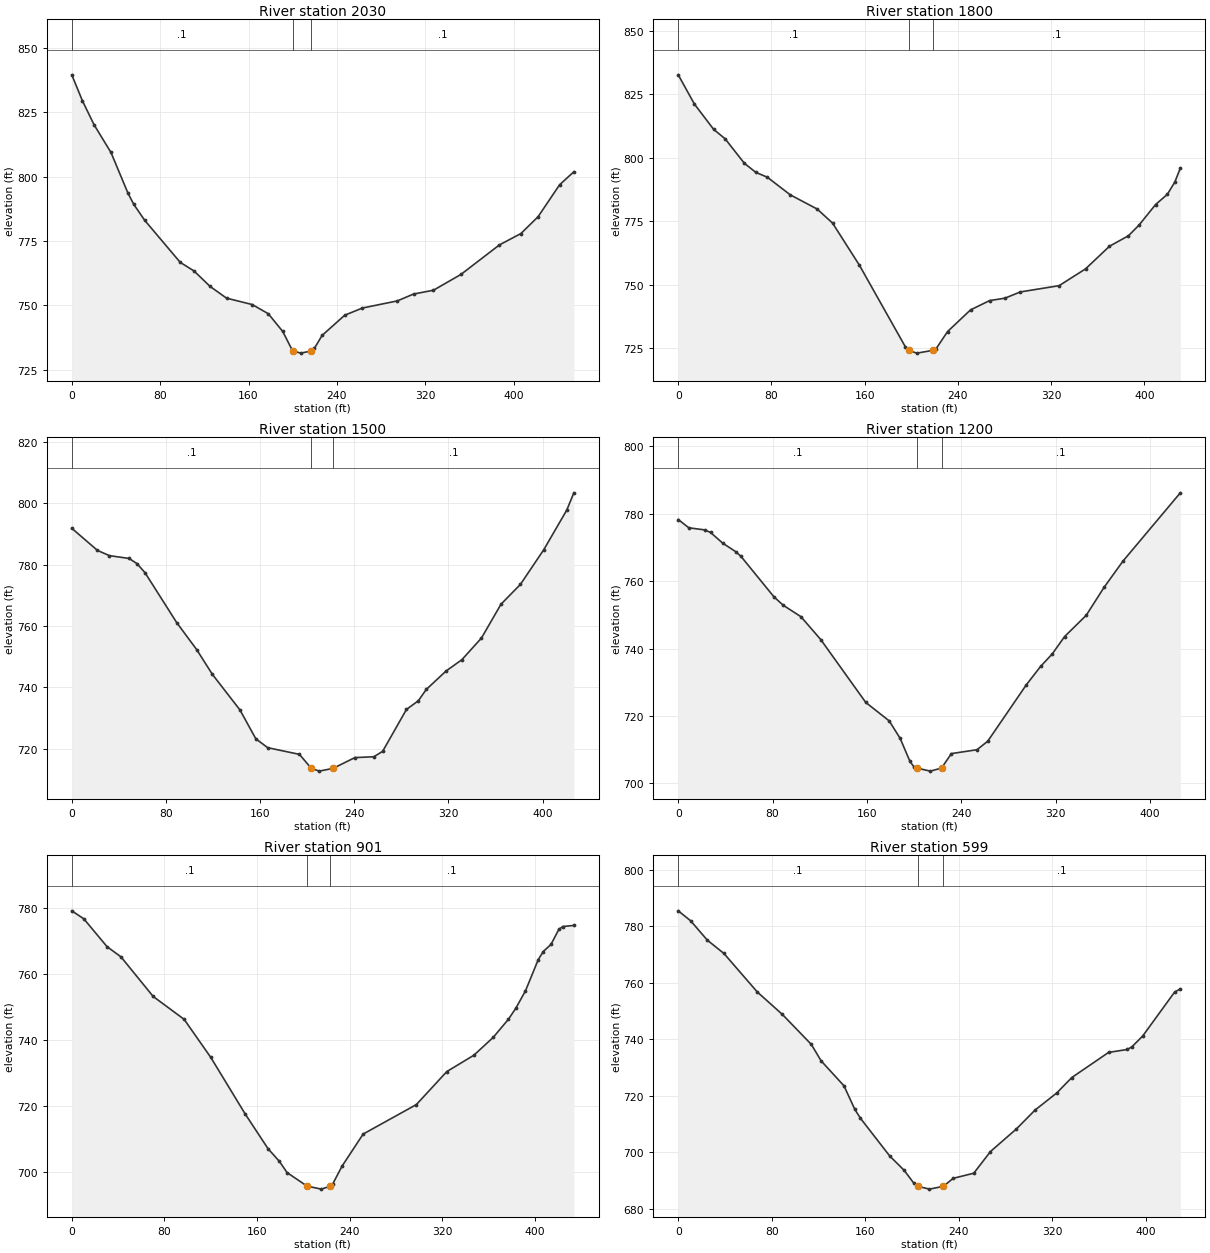
Type RM Length L Ch R = 1 ,2030    ,238.7,230.2,222.3
XS GIS Cut Line= 6
1627636.46529417470134.2272507351627584.66159199470221.248402158
1627526.09379575470283.9172400781627439.53294524470343.215021738
1627375.42316533470382.1375160761627301.63492708470429.159403661
#Sta/Elev= 30
       0  839.61     9.7  829.47    20.2  820.18    35.5  809.42    50.8  793.69
    56.1  789.27      66  783.07    98.2   766.7   110.7  763.36   125.1   757.4
   140.1   752.8   163.3  750.32   177.9  746.75     191  739.84  199.89732.3104
   207.3  731.43  216.72732.2614   219.6  733.26   226.6  738.32   247.1  746.17
     263  748.95   294.7  751.73   309.4   754.4   327.4  755.88   352.3  762.02
   387.1  773.49   406.6  777.92   422.1  784.44   441.6  796.87   454.5  801.93
#Mann= 3 ,-1,0
       0      .1       0  199.89    .045       0  216.72      .1       0
Bank Sta=199.89,216.72
XS Rating Curve= 0 ,0
Exp/Cntr(USF)=0,0
Exp/Cntr=0.3,0.1

Type RM Length L Ch R = 1 ,1800    ,297.6,300,300.7
XS GIS Cut Line= 6
  1627325.196005469993.3739593331627318.68453509470080.631330758
1627313.10383759 470155.423504011627305.66225143470255.146401674
1627302.64388476470330.1295194181627285.13309301470421.692000344
#Sta/Elev= 30
       0  832.67    13.9  821.14    30.4  811.18    40.2  807.49    56.7  797.84
    66.6  794.24    76.4  792.35    96.2  785.38   119.2  779.81   132.4  774.28
   155.4  757.72   194.9  725.52  197.58724.1394   204.7  723.05  218.55724.1398
   221.2  724.75   231.1  731.55   250.8  740.08   267.2  743.75   280.4   744.7
   293.5  747.15   326.8  749.62   349.5  756.24     370  765.14   386.3  769.28
   395.3  773.44   409.6  781.58   419.7  785.61   426.1  790.44   430.8   795.9
#Mann= 3 ,-1,0
       0      .1       0  197.58    .045       0  218.55      .1       0
Bank Sta=197.58,218.55
XS Rating Curve= 0 ,0
Exp/Cntr(USF)=0,0
Exp/Cntr=0.3,0.1

Type RM Length L Ch R = 1 ,1500    ,309.8,300,288.5
XS GIS Cut Line= 6
1627067.13057625469966.334971428  1627047.633568 470051.63532576
1627030.92165917470124.7496808321627008.63889535 470222.23537825
 1626991.9269865470295.3500614171626980.69308509 470383.64417617
#Sta/Elev= 30
       0  791.86    21.8  784.65    31.9  782.95    48.7  782.02    55.4  780.34
    62.2   777.4    89.1  761.15   106.1  752.34   119.4   744.3   142.9  732.66
   156.4  723.25   166.5  720.38   193.4  718.21  203.46713.6607   210.2  712.75
  222.07713.6603   240.5  717.16   256.6  717.43   264.1  719.21   284.3  732.84
   294.4  735.67   301.1  739.34   317.9  745.34   331.4  749.05     348  756.09
   364.6  767.11   381.1  773.57     401   784.9   420.5  797.79   426.5   803.4
#Mann= 3 ,-1,0
       0      .1       0  203.46    .045       0  222.07      .1       0
Bank Sta=203.46,222.07
XS Rating Curve= 0 ,0
Exp/Cntr(USF)=0,0
Exp/Cntr=0.3,0.1

Type RM Length L Ch R = 1 ,1200    ,285.9,299,304.5
XS GIS Cut Line= 6
1626595.54228058470120.9829560821626663.14778842470177.156400174
1626719.80023417470226.3118136671626794.54155451470292.748360589
1626850.59721668 470342.575688751626910.02820018470407.256989837
#Sta/Elev= 30
       0  778.27       9  775.81    22.3   775.2    27.4  774.43    37.7  771.27
    48.6  768.76    53.1  767.38    81.2  755.31      89  752.84     104  749.45
   120.8  742.67     159     724   178.9  718.52   188.2  713.31   196.5  706.48
   199.8  704.92  202.16704.5347   213.8  703.62  223.24 704.533   231.6  708.82
   253.3  709.97   262.4  712.49   295.1  729.21   307.2  734.67   317.1  738.38
   327.6  743.55   345.9  749.84   361.1  758.17   377.1  765.94   425.7  786.19
#Mann= 3 ,-1,0
       0      .1       0  202.16    .045       0  223.24      .1       0
Bank Sta=202.16,223.24
XS Rating Curve= 0 ,0
Exp/Cntr(USF)=0,0
Exp/Cntr=0.3,0.1

Type RM Length L Ch R = 1 ,901     ,311.3,302.3,297.8
XS GIS Cut Line= 6
1626511.13332868470190.6179874241626527.39773184470282.397331417
 1626520.0837701470357.4555802491626515.00832093 470457.34580043
1626514.18286325 470532.356805251626532.21629176470620.338912755
#Sta/Elev= 30
       0  779.25    10.4  776.83    30.4  768.39    42.5  765.27    70.3  753.25
      97  746.32     120  734.77   149.7   717.6   169.5  707.03   179.3  703.18
   185.9  699.79  203.13695.6921   215.5  694.77  223.34 695.692   225.3  696.34
   233.4  701.77   251.6  711.49   297.5  720.43   323.8  730.45   347.2  735.42
   363.9  740.84     377  746.33   383.3  749.62   391.7  754.93   402.8  764.46
   407.1   766.9   413.8  769.07   420.5   773.6   423.9  774.48   433.5  774.82
#Mann= 3 ,-1,0
       0      .1       0  203.13    .045       0  223.34      .1       0
Bank Sta=203.13,223.34
XS Rating Curve= 0 ,0
Exp/Cntr(USF)=0,0
Exp/Cntr=0.3,0.1

Type RM Length L Ch R = 1 ,599     ,143.8,151.8,159.5
XS GIS Cut Line= 6
1626153.64979167470361.6914641711626189.59000851470445.871085837
1626236.97541243470504.6829760821626297.58880825470584.576189011
1626341.25374718470645.5111065061626392.19360593470716.599875093
#Sta/Elev= 30
       0   785.5    10.6  781.98    24.9  775.11    39.1   770.4    67.7  756.74
    89.1  748.81   113.9  738.19   122.3  732.36   141.9  723.49   151.2  715.13
     156     712     181  698.66   193.3  693.61   201.6  689.05  205.46687.8846
     215   686.9  226.93687.8849   235.4  690.73     253  692.54   267.3  700.23
   289.4  708.19   305.5  714.93     324  720.96   336.9  726.43   368.4  735.34
   384.5  736.38   388.5  737.38   397.6  741.15   424.9   756.7   429.8  757.84
#Mann= 3 ,-1,0
       0      .1       0  205.46    .045       0  226.93      .1       0
Bank Sta=205.46,226.93
XS Rating Curve= 0 ,0
Exp/Cntr(USF)=0,0
Exp/Cntr=0.3,0.1

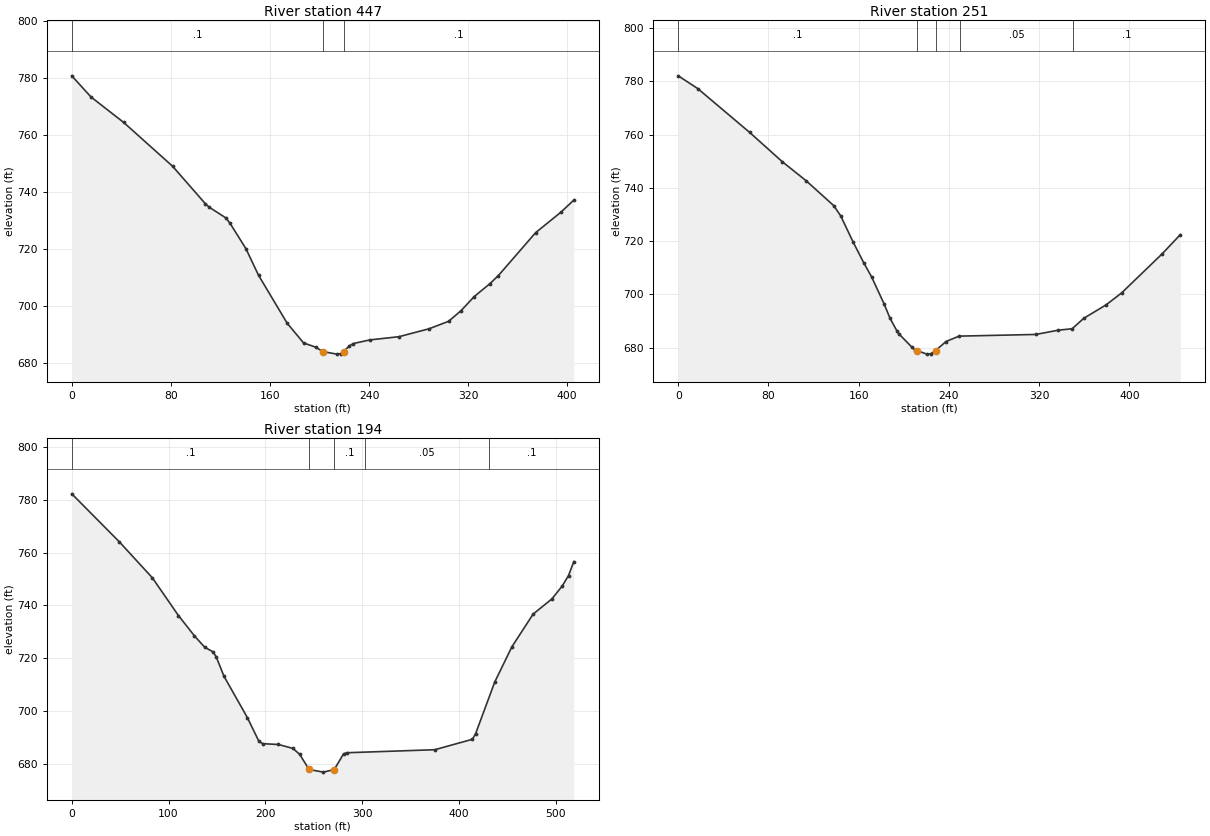
Type RM Length L Ch R = 1 ,447     ,194.1,196,197.7
XS GIS Cut Line= 4
1626113.36988455 470378.982028971626132.37830382470555.241916738
1626110.77782738470664.9723370641626133.24232288470779.022852679
#Sta/Elev= 30
       0  780.67    15.5  773.26    41.9  764.33    81.5  748.91   107.9  735.78
   111.2  734.51   124.4  730.84   127.7     729   140.6  720.05   150.8   710.7
   173.9   693.9   187.2  686.95   196.8  685.51  202.67683.9446     214  683.04
   217.3  683.25  219.52 683.929     224  685.89   227.3  686.75   240.7  688.03
   264.1  689.15   288.4  691.92   304.2  694.54   314.3  698.28   324.9  703.21
   337.7  707.78   344.4  710.57   374.5  725.64   394.8  732.78   405.4  737.08
#Mann= 3 ,-1,0
       0      .1       0  202.67    .045       0  219.52      .1       0
Bank Sta=202.67,219.52
XS Rating Curve= 0 ,0
Exp/Cntr(USF)=0,0
Exp/Cntr=0.3,0.1

Type RM Length L Ch R = 1 ,251     ,56.8,56.7,57.2
XS GIS Cut Line= 4
1626095.22548434470375.5259527391625952.66233982470500.808716104
1625886.99689144470652.0120511991625876.62866275470741.870033199
#Sta/Elev= 30
       0   782.1    17.3  777.31    63.4  760.82    92.3  749.83   113.4   742.7
   137.9  733.34     144  729.52   155.1  719.64   164.4  711.93   171.4  706.62
   182.6  696.35   187.7  691.12     194   686.2   195.4   685.3   207.4  680.09
   209.7  679.22  211.74678.9294   220.4  677.59     224  677.75   228.2678.9352
   237.4  682.33     249  684.35     317  684.98   337.1  686.59   349.2  687.12
   359.5  691.04   379.3  696.09   393.1  700.59   428.9  715.21   445.1  722.45
#Mann= 5 ,-1,0
       0      .1       0  211.74    .045       0   228.2      .1       0
  249.79     .05       0  349.79      .1       0
Bank Sta=211.74,228.2
XS Rating Curve= 0 ,0
Exp/Cntr(USF)=0,0
Exp/Cntr=0.3,0.1

Type RM Length L Ch R = 1 ,194     ,,,
XS GIS Cut Line= 5
1626079.57612093 470356.269887091625896.50110107470485.256373066
1625873.17258652470550.0578023921625825.65153834470647.691955911
1625810.16410569470764.103233258
#Sta/Elev= 30
       0  782.24    49.1  764.07    83.3   750.4   110.2  736.12   126.7  728.43
   137.3  724.12   145.9  722.36   149.3  720.41   157.3  713.09   181.4  697.46
   193.4  688.41   197.5  687.53   213.5  687.24   228.5  685.75   235.5   683.5
   245.2  677.77   259.9  676.76  271.17677.7152   280.8  683.65   284.3  684.11
   375.1  685.25     414  689.21   417.3  691.35   437.1  710.95   454.8  724.27
   476.8  736.69     496  742.37   506.6  747.19   513.3  751.27   518.8  756.56
#Mann= 5 ,-1,0
       0      .1       0   245.2    .045       0  271.17      .1       0
  302.82     .05       0  431.41      .1       0
Bank Sta=245.2,271.17
XS Rating Curve= 0 ,0
Exp/Cntr(USF)=0,0
Exp/Cntr=0.3,0.1
LCMann Table=0

Chan Stop Cuts=-1
Use User Specified Reach Order=0
Composite Channel Slope=5